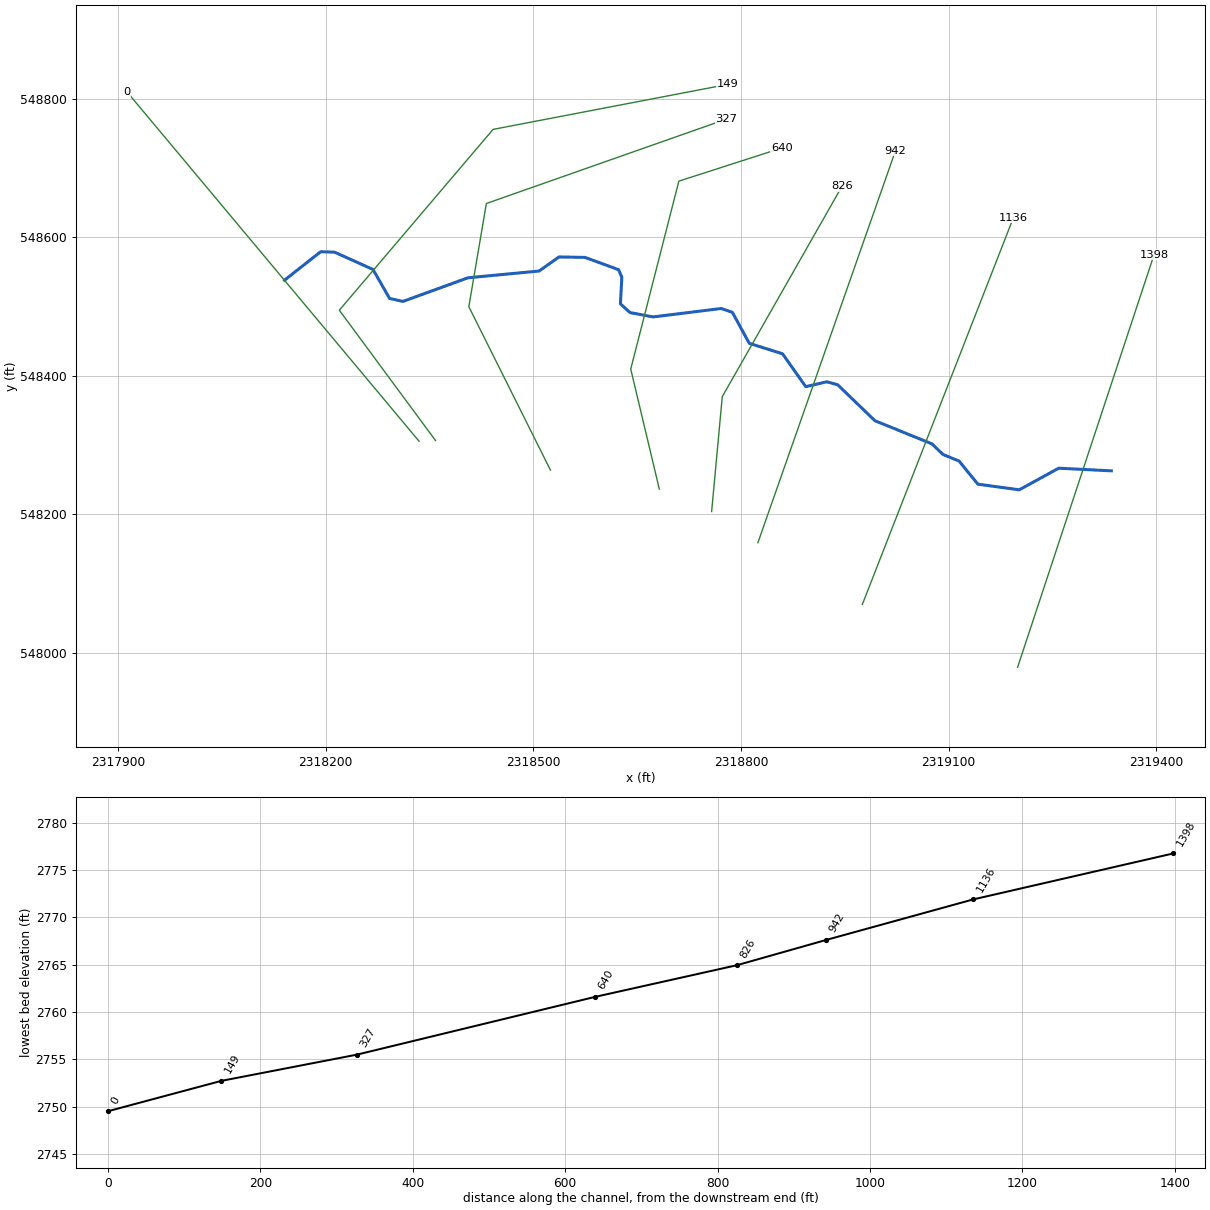
--- DEERCKT1.prj (project) ---

Proj Title=DEERCKT1
Current Plan=p01
Default Exp/Contr=0,0
English Units
Geom File=g01
Flow File=f01
Plan File=p01
Background Map Layer=Inundation Boundary (01pct Value_0)
BEGIN DESCRIPTION:
----------MODEL BY WOOD PLC 2021----------
Stream Name: Deer Creek Tributary 1
Flood Zone: Enhanced Approximate
Pocahontas County, WV
HEC-RAS Version: RAS 6.1.0
Vertical Datum: NAVD88
Projection: NAD 1983 StatePlane West Virginia S FIPS 4702 (US Feet)
Terrain: 1-meter LIDAR (FEMA Region III 3DEP collected 2016-2018)
Land Use: 2019 NLCD
Hydrologic Method:
WV SIR2010-5033 regression equations
Model Notes:
Coincident peak KWSEL tie in with Deer Creek XS 91374
END DESCRIPTION:
DSS File=dss
DSS Export Rating Curves= 0
DSS Export Rating Curve Sorted= 0
DSS Export Volume Flow Curves= 0
DXF OffsetX= 0
DXF OffsetY= 0
DXF ScaleX= 0
DXF ScaleY= 0

--- DEERCKT1.p01 (plan) ---

Plan Title=Floodplain
Program Version=6.10
Short Identifier=Floodplain
Geom File=g01
Flow File=f01
Subcritical Flow
K Sum by GR= 0
Std Step Tol= 0.01
Critical Tol= 0.01
Num of Std Step Trials= 20
Max Error Tol= 0.3
Flow Tol Ratio= 0.001
Split Flow NTrial= 30
Split Flow Tol= 0.02
Split Flow Ratio= 0.02
Log Output Level= 0
Friction Slope Method= 1
Unsteady Friction Slope Method= 2
Unsteady Bridges Friction Slope Method= 1
Parabolic Critical Depth
Global Vel Dist= 0 , 0 , 0
Global Log Level= 0
CheckData=True
Encroach Param=-1 ,0,0, 0
Computation Interval=0.1SEC
Output Interval=1SEC
Instantaneous Interval=Max Profile
Mapping Interval=1HOUR
Computation Time Step Use Courant=        0
Computation Time Step Use Time Series=    0
Computation Time Step Count To Double=0
Computation Time Step Max Doubling=0
Computation Time Step Max Halving=0
Computation Time Step Residence Courant=0
Run HTab= 0
Run UNet= 0
Run Sediment= 0
Run PostProcess= 0
Run WQNet= 0
Run RASMapper=-1
UNET Theta= 0
UNET Theta Warmup= 0
UNET ZTol= 0
UNET ZSATol= 0
UNET MxIter= 0
UNET Max Iter WO Improvement= 0
UNET MaxInSteps= 0
UNET DtIC= 0
UNET DtMin= 0
UNET MaxCRTS= 0
UNET WFStab= 0
UNET SFStab= 0
UNET WFX= 1
UNET SFX= 1
UNET Gravity=32.174
UNET 1D Methodology=Finite Difference
UNET DSS MLevel= 1
UNET Pardiso=0
UNET DZMax Abort= 0
UNET Use Existing IB Tables= 0
UNET Froude Reduction=False
UNET Froude Limit= 0
UNET Froude Power= 0
UNET D1 Cores= 0
UNET WindReference=Eulerian
UNET WindDragFormulation=Hsu (1988)
UNET D2 Coriolis=0
UNET D2 Cores= 0
UNET D2 Theta= 1
UNET D2 Theta Warmup= 1
UNET D2 Z Tol= 0.01
UNET D2 Volume Tol= 0.01
UNET D2 Max Iterations= 20
UNET D2 Equation= 0
UNET D2 RampUpFraction=0.1
UNET D2 TimeSlices= 1
UNET D2 Turbulence Formulation=Non-Conservative (original)
UNET D2 Eddy Viscosity=0.3
UNET D2 Transverse Eddy Viscosity=0.1
UNET D2 Smagorinsky Mixing=0
UNET D2 BCVolumeCheck=0
UNET D2 Cores=0
UNET D2 SolverType=PARDISO (Direct)
UNET D2 Minimum Iterations= 2147483647
UNET D2 Maximum Iterations= 2147483647
UNET D2 Restart Number= 10
UNET D2 Relaxation Coeff=1.3
UNET D2 SOR Precondition Iterations= 10
UNET D2 ILUT Maximum Fill= 8
UNET D2 ILUT Tolerance=1E-08
UNET D1D2 MaxIter= 0
UNET D1D2 ZTol=0.01
UNET D1D2 QTol=0.1
UNET D1D2 MinQTol=1
DSS File=dss
Write IC File= 0
Write IC File at Fixed DateTime=0
Write IC File at Sim End=0
Echo Input=False
Echo Parameters=False
Echo Output=False
Write Detailed= 0
HDF Write Warmup=0
HDF Write Time Slices=0
HDF Flush=0
HDF Compression= 1
HDF Chunk Size= 1
HDF Spatial Parts= 1
HDF Use Max Rows=0
HDF Fixed Rows= 1
Calibration Method= 0
Calibration Iterations= 20
Calibration Max Change=0.05
Calibration Tolerance=0.2
Calibration Maximum=1.5
Calibration Minimum=0.5
Calibration Optimization Method= 1
WQ AD Non Conservative
WQ ULTIMATE=-1
WQ Max Comp Step=1HOUR
WQ Output Interval=15MIN
WQ Output Selected Increments= 0
WQ Output face flow=0
WQ Output face velocity=0
WQ Output face area=0
WQ Output face dispersion=0
WQ Output cell volume=0
WQ Output cell surface area=0
WQ Output cell continuity=0
WQ Output cumulative cell continuity=0
WQ Output face conc=0
WQ Output face dconc_dx=0
WQ Output face courant=0
WQ Output face peclet=0
WQ Output face adv mass=0
WQ Output face disp mass=0
WQ Output cell mass=0
WQ Output cell source sink temp=0
WQ Output nsm pathways=0
WQ Output nsm derived pathways=0
WQ Create Restart=0
WQ Fixed Restart=0
WQ System Summary=0
WQ Write To DSS=0
Sorting and Armoring Iterations= 10
XS Update Threshold= 0.02
Bed Roughness Predictor= 0
Hydraulics Update Threshold= 0.02
Energy Slope Method= 1
Volume Change Method= 1
Sediment Retention Method= 0
Sediment TS Multiplier= 1
Warm Up Method= 0
XS Weighting Method= 0
Number of US Weighted Cross Sections= 1
Number of DS Weighted Cross Sections= 1
Upstream XS Weight=0
Main XS Weight=1
Downstream XS Weight=0
Number of DS XS's Weighted with US Boundary= 1
Upstream Boundary Weight= 1
Weight of XSs Associated with US Boundary= 0
Number of US XS's Weighted with DS Boundary= 1
Downstream Boundary Weight= 0.5
Weight of XSs Associated with DS Boundary= 0.5
Percentile Method= 0
Sediment Output Level= 3
Mass or Volume Output= 0
Output Increment Type= 1
Profile and TS Output Increment= 1
Transport Output Increment 1
XS Output Flag= 0
XS Output Increment= 10
Read HDF5 Sediment Hotstart= 0
Sediment Hotstart Type= 0
Write Gradation File= 0
Read Gradation Hotstart= 0
Write HDF5 File= 1
Write Binary Output= 1
Write DSS Sediment File= 0
DSS Sediment Output Type= 1
SV Curve= 0
Specific Gage Flag= 0
Subcell Erosion Methods= 0
Subcell Deposition Methods= 0
Advection Scheme= 1
Matrix Solver= 0
Implicit Weighting Factor= 1
Maximum Outer Loop Convergence Iterations= 5
Convergence Maximum Absolute= 0.001
Convergence RMSE= 0.0001
Grain Fractions Max Abs Error= 0.001
Max Subgrid Regions= 1
Max Subgrid Length Scale= 3.402823E+38
Initial Layer Thickness= 3.402823E+38
Min Layer Thickness= 3.402823E+38
Max Layer Thickness= 3.402823E+38
Number of Layers= 5

--- DEERCKT1.f01 (steady flow) ---

Flow Title=Flow
Program Version=6.10
Number of Profiles= 6
Profile Names=01pct,10pct,04pct,02pct,0_2pct,01plus
River Rch & RM=DEERCKT1,Main            ,1398
     426     222     297     360     598     630
River Rch & RM=DEERCKT1,Main            ,0
     837     449     593     711    1160    1240
Boundary for River Rch & Prof#=DEERCKT1,Main            , 1
Up Type= 0
Dn Type= 1
Dn Known WS=2754
Boundary for River Rch & Prof#=DEERCKT1,Main            , 2
Up Type= 0
Dn Type= 1
Dn Known WS=2752.8
Boundary for River Rch & Prof#=DEERCKT1,Main            , 3
Up Type= 0
Dn Type= 1
Dn Known WS=2753.6
Boundary for River Rch & Prof#=DEERCKT1,Main            , 4
Up Type= 0
Dn Type= 1
Dn Known WS=2753.8
Boundary for River Rch & Prof#=DEERCKT1,Main            , 5
Up Type= 0
Dn Type= 1
Dn Known WS=2754.4
Boundary for River Rch & Prof#=DEERCKT1,Main            , 6
Up Type= 0
Dn Type= 1
Dn Known WS=2754.5
DSS Import GetInterval= 0
DSS Import GetPeak= 0
DSS Import FillOption= 0

--- DEERCKT1.g01 (geometry) ---

Geom Title=Geometry
Program Version=6.10

River Reach=DEERCKT1        ,Main
Reach XY= 30
2319335.27564619548262.5849605952319259.23105398548266.414599895
2319202.25740197548235.1817837512319142.48623748548243.306019709
2319115.21201679548276.7701344792319091.99991405548286.248409748
2319076.13831055548301.5297106952318993.69500002548335.009000003
2318939.73696384548387.0359788692318924.12676671548391.224080533
2318893.71400003548384.2580000162318860.19659583 548431.69861342
2318812.10359778548446.8648564372318787.73088992548491.606184438
2318771.71453905548497.1770890952318673.17916298548484.990735173
2318639.92782581548491.2580029072318625.96297573548503.817912251
2318627.99699999548542.4190000152318623.19499999548553.287000015
2318574.80142182548571.0059769452318537.20076175 548571.62238121
 2318508.4892942548551.3193186972318405.59900001548541.503000006
2318311.77157934548507.409533635 2318292.4281604548511.665085807
2318268.44700001 548553.57100001     2318212.799548578.604000002
2318192.77993166548579.1679977182318140.49587254548538.013624579

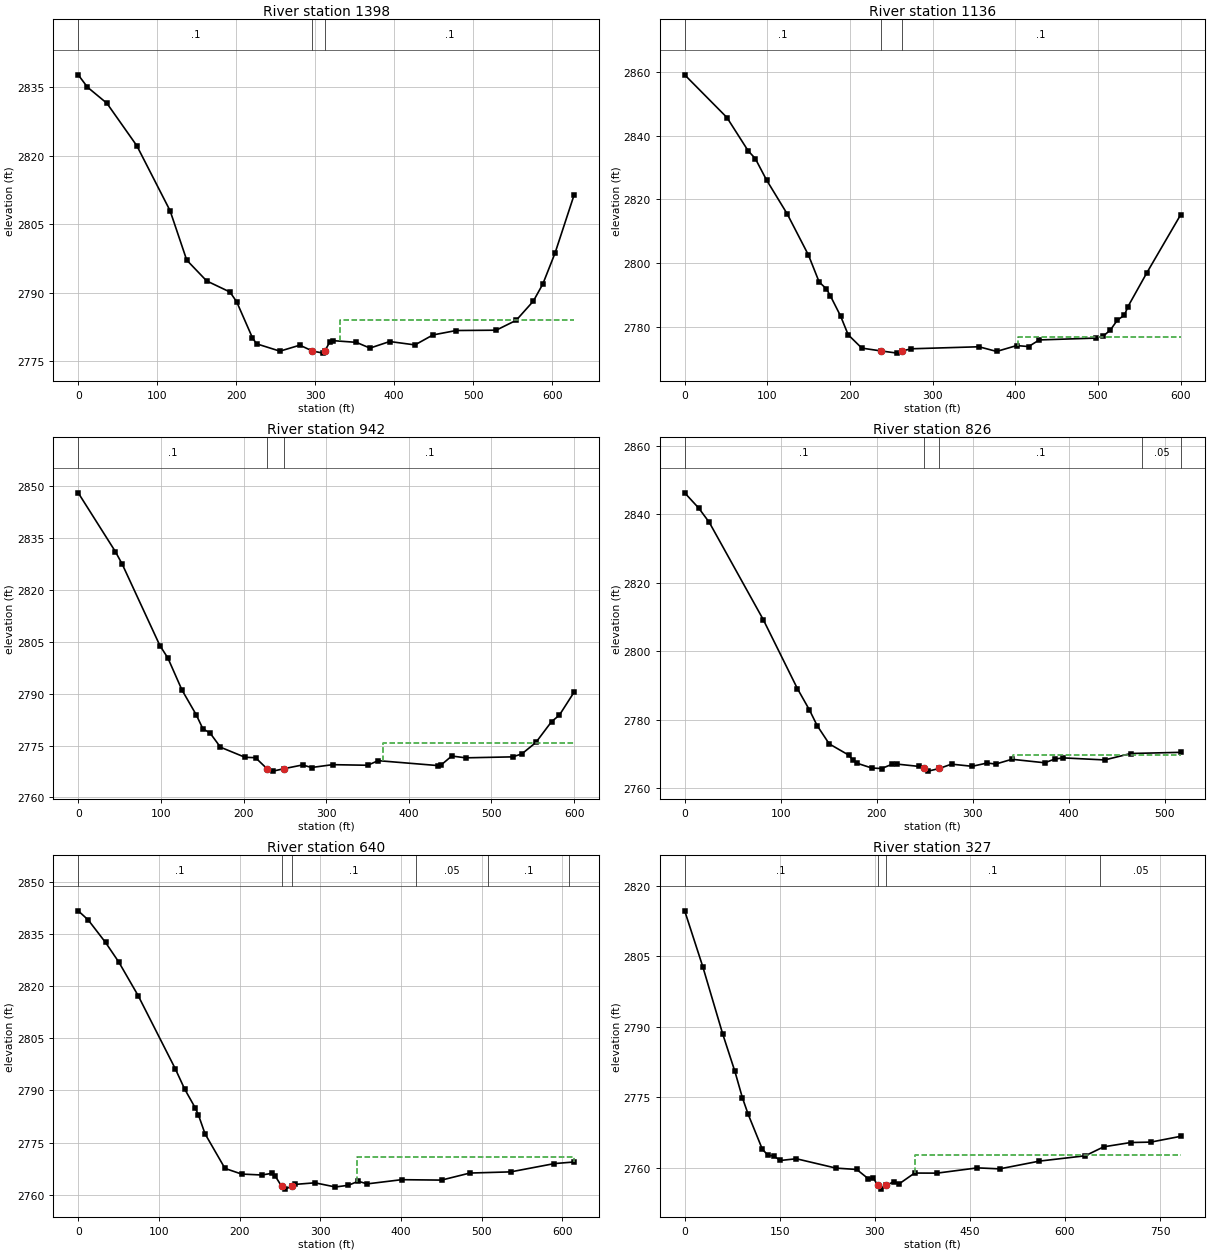
Type RM Length L Ch R = 1 ,1398    ,262.6,262.6,262.6
XS GIS Cut Line= 2
2319199.85160872547978.7623453662319397.03008157548574.937257388
#Sta/Elev= 30
       0 2837.67    11.7 2834.97    36.3 2831.45    74.2 2822.15   116.3 2807.93
   137.4 2797.11   162.6 2792.56   192.1 2790.13   200.6    2788   220.6 2780.11
   225.8 2778.79   255.4 2777.18   280.6 2778.49   296.6 2777.21   310.1 2776.75
   312.4 2777.26   318.5 2779.19   322.7 2779.48   352.2 2779.11   369.4 2777.85
   394.4 2779.29   426.4 2778.55   449.1 2780.73   478.6  2781.7   529.2 2781.77
   554.5 2783.93   576.2 2788.12   588.2 2791.85   603.7 2798.63627.9362 2811.41
#Mann= 3 ,-1,0
       0      .1       0   296.6    .045       0   312.4      .1       0
#XS Ineff= 2 , 0
                          331.27         2783.91
Permanent Ineff=
       F       F
Bank Sta=296.6,312.4
XS Rating Curve= 0 ,0
Exp/Cntr(USF)=0,0
Exp/Cntr=0.3,0.1

Type RM Length L Ch R = 1 ,1136    ,193.7,193.7,193.7
XS GIS Cut Line= 2
2318975.51537465 548069.609815552319193.80455933 548628.49247931
#Sta/Elev= 30
       0    2859    51.1 2845.64    76.8 2835.21    85.4  2832.8      99  2826.1
   124.1 2815.44   149.8 2802.55   162.7 2794.15   171.3 2792.04   176.2 2789.86
   188.6 2783.51   197.8 2777.64   214.3 2773.46   237.7 2772.57   257.2 2771.89
   262.7 2772.56   274.4 2773.25     356 2773.88   377.4 2772.42   401.6 2774.25
   416.1 2773.95     429 2776.02   497.4  2776.6   506.6 2777.27   514.9 2779.09
   523.4 2782.19     532 2783.78   536.3 2786.46   559.1 2797.02     600 2815.18
#Mann= 3 ,-1,0
       0      .1       0   237.7    .045       0   262.7      .1       0
#XS Ineff= 2 , 0
                          403.08         2777.02
Permanent Ineff=
       F       F
Bank Sta=237.7,262.7
XS Rating Curve= 0 ,0
Exp/Cntr(USF)=0,0
Exp/Cntr=0.3,0.1

Type RM Length L Ch R = 1 ,942     ,117.6,116.2,108.3
XS GIS Cut Line= 2
2318824.60673359548158.7677307562319023.30791429  548724.9106816
#Sta/Elev= 30
       0 2848.16    44.9 2831.17    53.4 2827.43    98.8 2803.94   108.5 2800.33
   125.5 2791.09   142.8 2783.89   150.9 2779.81   159.4 2778.66   172.1 2774.52
   201.8  2771.6   214.5 2771.48   228.2 2768.34   235.7 2767.59   249.4 2768.32
   271.4 2769.38   282.3 2768.64   307.8 2769.46   350.2 2769.29   362.9 2770.62
     435  2769.2   439.2  2769.4   451.9 2771.96   468.9 2771.44   525.6 2771.72
   536.7 2772.57   553.7 2775.89   572.6  2781.9   582.1 2783.79     600 2790.48
#Mann= 3 ,0,0
       0      .1       0   228.2    .045       0   249.4      .1       0
#XS Ineff= 2 , 0
                          368.79         2775.61
Permanent Ineff=
       F       F
Bank Sta=228.2,249.4
XS Rating Curve= 0 ,0
Exp/Cntr(USF)=0,0
Exp/Cntr=0.3,0.1

Type RM Length L Ch R = 1 ,826     ,181.7,186.2,187.7
XS GIS Cut Line= 3
2318757.73817733548203.7489072592318773.10474724548369.707862226
2318946.23476816548673.965946333
#Sta/Elev= 30
       0 2846.25    14.6  2841.8    25.6 2837.63    81.8 2809.24   117.5 2789.02
     130 2782.81     138 2778.25   150.6  2772.9   170.7 2769.66   175.3 2768.16
   179.9 2767.22   194.9 2765.85   205.2  2765.7   215.5 2766.89   221.4 2766.99
   244.3 2766.31   248.9 2765.71   253.8 2764.94   265.3 2765.72     278 2766.98
   299.5 2766.35   315.2 2767.31     324    2767   340.9  2768.4   375.1 2767.38
   385.6 2768.47   394.4 2768.81   437.6 2768.21   464.8 2770.09   516.7 2770.43
#Mann= 5 ,-1,0
       0      .1       0   248.9    .045       0   265.3      .1       0
  476.67     .05       0  516.67      .1       0
#XS Ineff= 2 , 0
                          341.79         2769.72
Permanent Ineff=
       F       F
Bank Sta=248.9,265.3
XS Rating Curve= 0 ,0
Exp/Cntr(USF)=0,0
Exp/Cntr=0.3,0.1

Type RM Length L Ch R = 1 ,640     ,312.8,312.8,312.8
XS GIS Cut Line= 4
2318682.14932729 548236.250251252318640.84156492548409.644202438
 2318710.3643747 548681.158959552318859.00520952548729.042668608
#Sta/Elev= 30
       0 2841.75    12.4 2839.12    33.9 2832.63    50.3 2826.99    74.2 2817.36
   120.2 2796.31   131.9 2790.43   144.9 2785.05     149 2782.96   157.2 2777.52
   181.9 2767.56   202.5 2765.93   227.3 2765.66   239.7 2766.12   243.8 2765.51
   252.1  2762.4   256.2 2761.59   264.5 2762.38   268.6 2762.95   293.4 2763.41
   318.7 2762.21   334.7 2762.69   347.1 2763.86   358.1  2763.1   400.9 2764.31
   450.3 2764.19   485.4 2766.22   536.1 2766.56   590.3 2768.95   614.7 2769.41
#Mann= 6 ,-1,0
       0      .1       0   252.1    .045       0   264.5      .1       0
  418.25     .05       0  508.52      .1       0  608.52     .05       0
#XS Ineff= 2 , 0
                          345.35         2770.93
Permanent Ineff=
       F       F
Bank Sta=252.1,264.5
XS Rating Curve= 0 ,0
Exp/Cntr(USF)=0,0
Exp/Cntr=0.3,0.1

Type RM Length L Ch R = 1 ,327     ,177.8,177.8,177.8
XS GIS Cut Line= 4
2318524.83246527548263.6543021922318406.91898971548499.750959265
2318432.23977417548648.8482482662318778.63661692548770.646295517
#Sta/Elev= 30
       0 2814.67    28.5 2802.82    59.8 2788.56    79.2 2780.52    91.1 2774.89
   100.2 2771.38   122.4    2764   131.4 2762.66   140.3 2762.56   150.7 2761.57
   176.1 2761.94   238.7 2759.95   271.4 2759.66   289.7 2757.68   297.8  2757.8
   304.4 2756.29     310 2755.48   317.9 2756.34   330.3 2757.05   338.4 2756.61
   362.7  2758.9     398 2758.88   461.7    2760   496.9 2759.79   559.6 2761.44
   631.8 2762.57     661 2764.48   703.4 2765.39   735.3 2765.48   782.3 2766.71
#Mann= 4 ,-1,0
       0      .1       0   304.4    .045       0   317.9      .1       0
  655.14     .05       0
#XS Ineff= 2 , 0
                          362.54         2762.68
Permanent Ineff=
       F       F
Bank Sta=304.4,317.9
XS Rating Curve= 0 ,0
Exp/Cntr(USF)=0,0
Exp/Cntr=0.3,0.1

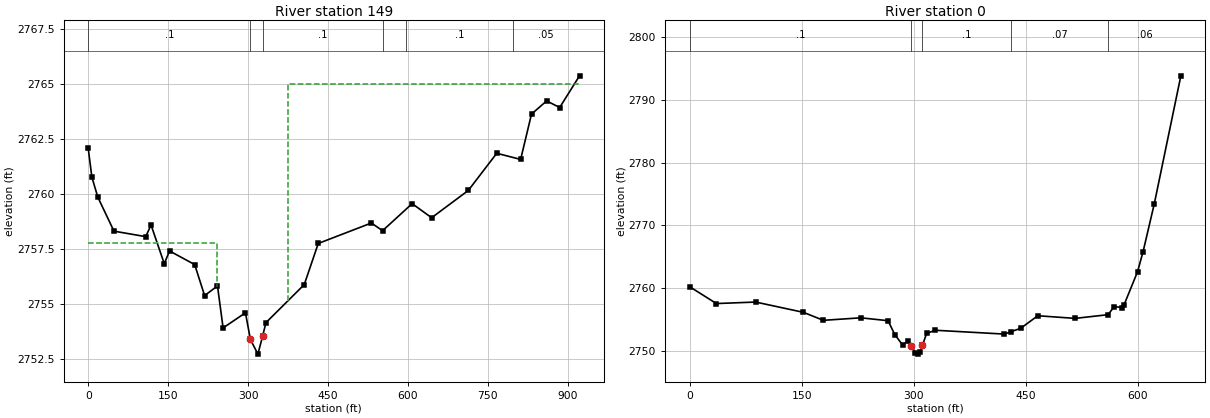
Type RM Length L Ch R = 1 ,149     ,148.9,148.9,148.9
XS GIS Cut Line= 4
2318358.81133415548306.3351831292318219.77792806548494.680930301
2318441.95742036 548755.967848652318780.71375707548820.904639489
#Sta/Elev= 30
       0 2762.06     6.8 2760.76    17.9 2759.85    48.3  2758.3   107.9 2758.05
   117.9 2758.58   142.7 2756.82   152.6  2757.4   199.8 2756.78   218.4 2755.37
   242.6 2755.81   253.1  2753.9   295.1 2754.59   304.3 2753.38   318.4 2752.71
   327.3 2753.53   333.5 2754.14   405.4 2755.87   431.7 2757.74   531.4 2758.67
   552.4 2758.32   607.9 2759.55   644.5 2758.91   713.3 2760.15   766.7 2761.84
   811.5 2761.56   831.9 2763.62   860.3 2764.22   884.8 2763.92     922 2765.36
#Mann= 6 ,-1,0
       0      .1       0   304.3    .045       0   327.3      .1       0
   554.1     .07       0  597.08      .1       0  797.08     .05       0
#XS Ineff= 2 , 0
          240.86 2757.77     375            2765
Permanent Ineff=
       F       F
Bank Sta=304.3,327.3
XS Rating Curve= 0 ,0
Exp/Cntr(USF)=0,0
Exp/Cntr=0.3,0.1

Type RM Length L Ch R = 1 ,0       ,194.6,195.6,196.6
XS GIS Cut Line= 2
 2318335.0005454548305.3834510562317913.37293236548809.655679281
#Sta/Elev= 30
       0 2760.24    35.9 2757.55    88.4 2757.79   152.4 2756.15     179 2754.88
   229.1 2755.28   265.6 2754.82   274.5 2752.62     285 2750.96   291.7 2751.57
   296.9 2750.87   302.1 2749.66   305.7  2749.5   308.5 2749.76   311.6 2750.88
   317.1 2752.79   328.7  2753.3   421.3 2752.69     4302753.075   442.9  2753.6
   465.9 2755.61   515.9 2755.19     560 2755.78   568.1 2757.08   578.5 2756.91
   581.2 2757.31   599.3  2762.6   606.7 2765.78   621.8 2773.45   657.3  2793.8
#Mann= 5 ,-1,0
       0      .1       0   296.9    .045       0   311.6      .1       0
     430     .07       0     560     .06       0
Bank Sta=296.9,311.6
XS Rating Curve= 0 ,0
Exp/Cntr=0.3,0.1
LCMann Table=0

Chan Stop Cuts=-1
Use User Specified Reach Order=0
Composite Channel Slope=5